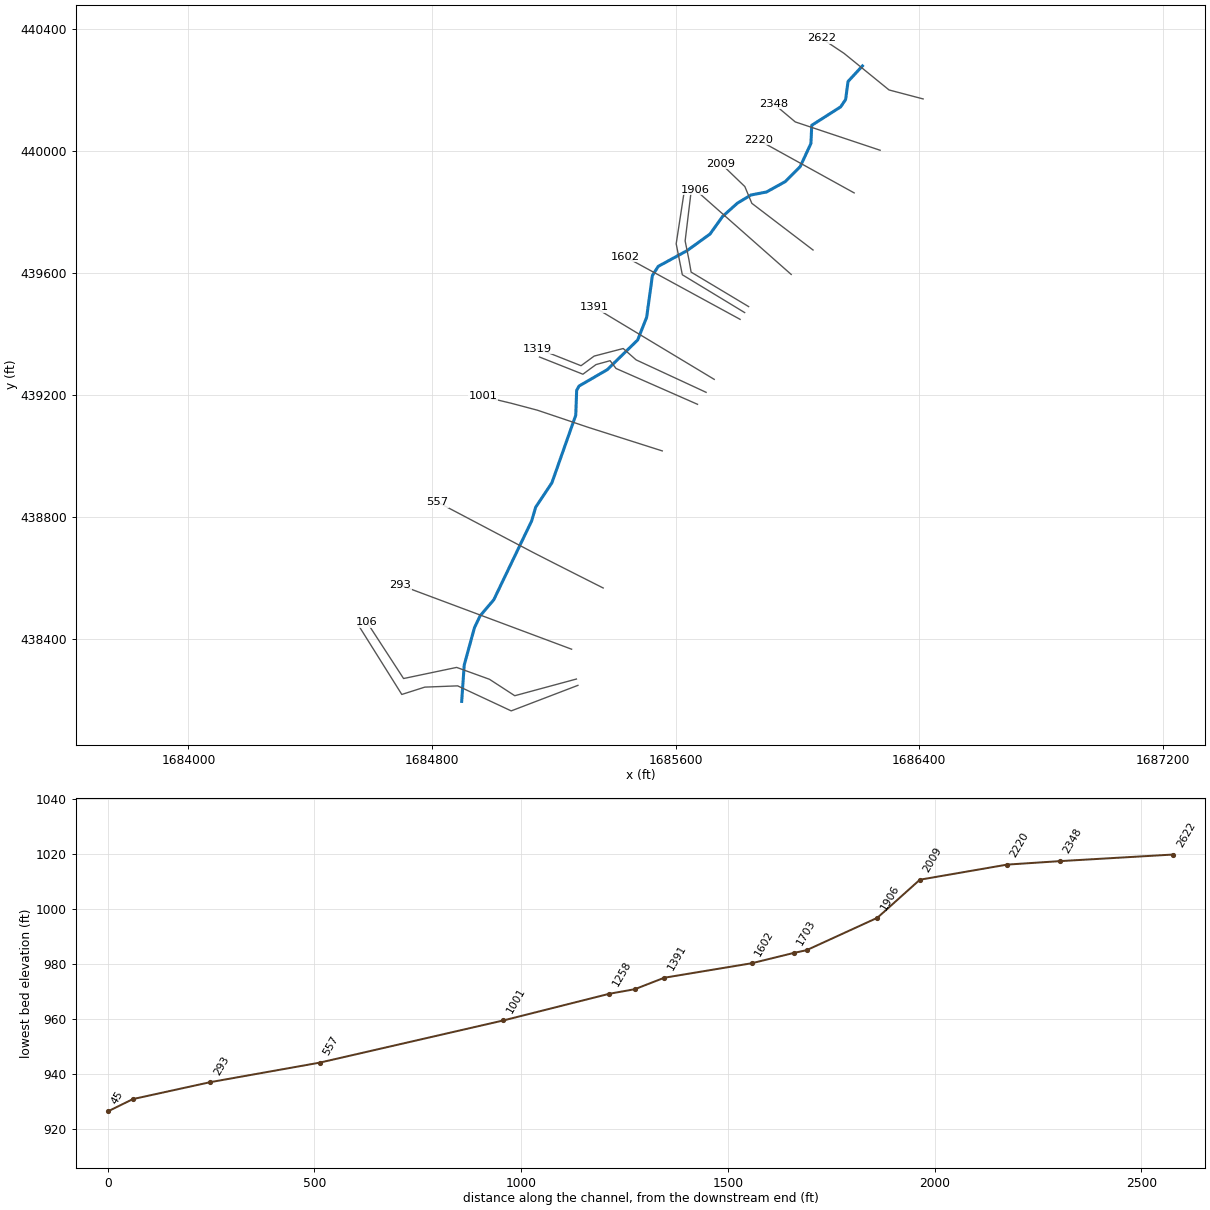
--- WOLFRN.prj (project) ---

Proj Title=WOLFRN
Current Plan=p01
Default Exp/Contr=0,0
English Units
Geom File=g01
Flow File=f01
Plan File=p01
BEGIN DESCRIPTION:
---------- MODELED AS PART OF WVEMD CTP PROGRAM, 2023----------
Stream Name: Wolf Run
Flood Zone:  AFH
Wetzel County, WV
HEC-RAS Version: RAS 6.3
Vertical Datum: NAVD88
Projection: NAD 1983 StatePlane West Virginia S FIPS 4702 (US Feet)
Terrain: 1-meter West Virginia FEMA R3 South Central (collected 2018-2020)
Land Use: 2019 NLCD
Hydrologic Method:
WV SIR2010-5033 regression equations
Additional Model Notes:
None
END DESCRIPTION:
DSS Export Rating Curves= 0
DSS Export Rating Curve Sorted= 0
DSS Export Volume Flow Curves= 0
DXF OffsetX= 0
DXF OffsetY= 0
DXF ScaleX= 0
DXF ScaleY= 0

--- WOLFRN.p01 (plan) ---

Plan Title=Floodplain
Program Version=6.30
Short Identifier=Floodplain
Geom File=g01
Flow File=f01
Subcritical Flow
K Sum by GR= 0
Std Step Tol= 0.01
Critical Tol= 0.01
Num of Std Step Trials= 20
Max Error Tol= 0.3
Flow Tol Ratio= 0.001
Split Flow NTrial= 30
Split Flow Tol= 0.02
Split Flow Ratio= 0.02
Log Output Level= 0
Friction Slope Method= 1
Unsteady Friction Slope Method= 2
Unsteady Bridges Friction Slope Method= 1
Parabolic Critical Depth
Global Vel Dist= 0 , 0 , 0
Global Log Level= 0
CheckData=True
Encroach Param=-1 ,0,0, 0
Mapping Interval=1HOUR
Computation Time Step Use Courant=        0
Computation Time Step Use Time Series=    0
Computation Time Step Count To Double=0
Computation Time Step Max Doubling=0
Computation Time Step Max Halving=0
Computation Time Step Residence Courant=0
Run HTab= 0
Run UNet= 0
Run Sediment= 0
Run PostProcess= 0
Run WQNet= 0
Run RASMapper= 0
UNET Theta= 0
UNET Theta Warmup= 0
UNET ZTol= 0
UNET ZSATol= 0
UNET MxIter= 0
UNET Max Iter WO Improvement= 0
UNET MaxInSteps= 0
UNET DtIC= 0
UNET DtMin= 0
UNET MaxCRTS= 0
UNET WFStab= 0
UNET SFStab= 0
UNET WFX= 1
UNET SFX= 1
UNET Gravity=32.17405
UNET 1D Methodology=Finite Difference
UNET DSS MLevel= 1
UNET Pardiso=0
UNET DZMax Abort= 0
UNET Use Existing IB Tables= 0
UNET Froude Reduction=False
UNET Froude Limit= 0
UNET Froude Power= 0
UNET D1 Cores= 0
UNET WindReference=Eulerian
UNET WindDragFormulation=Hsu (1988)
UNET D2 Coriolis=0
UNET D2 Cores= 0
UNET D2 Theta= 1
UNET D2 Theta Warmup= 1
UNET D2 Z Tol= 0.01
UNET D2 Volume Tol= 0.01
UNET D2 Max Iterations= 20
UNET D2 Equation= 0
UNET D2 RampUpFraction=0.1
UNET D2 TimeSlices= 1
UNET D2 Turbulence Formulation=Non-Conservative (original)
UNET D2 Eddy Viscosity=0.3
UNET D2 Transverse Eddy Viscosity=0.1
UNET D2 Smagorinsky Mixing=0
UNET D2 BCVolumeCheck=0
UNET D2 Cores=0
UNET D2 SolverType=PARDISO (Direct)
UNET D2 Minimum Iterations= 3
UNET D2 Maximum Iterations= 30
UNET D2 Restart Number= 10
UNET D2 Relaxation Coeff=1.3
UNET D2 SOR Precondition Iterations= 10
UNET D2 ILUT Maximum Fill= 8
UNET D2 ILUT Tolerance=1E-08
UNET D2 Convergence Tolerance=0.00001
UNET D1D2 MaxIter= 0
UNET D1D2 ZTol=0.01
UNET D1D2 QTol=0.1
UNET D1D2 MinQTol=1
Write IC File= 0
Write IC File at Fixed DateTime=0
Write IC File at Sim End=0
Echo Input=False
Echo Parameters=False
Echo Output=False
Write Detailed= 0
HDF Write Warmup=0
HDF Write Time Slices=0
HDF Flush=0
HDF Compression= 1
HDF Chunk Size= 1
HDF Spatial Parts= 1
HDF Use Max Rows=0
HDF Fixed Rows= 1
Calibration Method= 0
Calibration Iterations= 20
Calibration Max Change=0.05
Calibration Tolerance=0.2
Calibration Maximum=1.5
Calibration Minimum=0.5
Calibration Optimization Method= 1
WQ AD Non Conservative
WQ ULTIMATE=-1
WQ Max Comp Step=1HOUR
WQ Output Interval=15MIN
WQ Output Selected Increments= 0
WQ Output face flow=0
WQ Output face velocity=0
WQ Output face area=0
WQ Output face dispersion=0
WQ Output cell volume=0
WQ Output cell surface area=0
WQ Output cell continuity=0
WQ Output cumulative cell continuity=0
WQ Output face conc=0
WQ Output face dconc_dx=0
WQ Output face courant=0
WQ Output face peclet=0
WQ Output face adv mass=0
WQ Output face disp mass=0
WQ Output cell mass=0
WQ Output cell source sink temp=0
WQ Output nsm pathways=0
WQ Output nsm derived pathways=0
WQ Create Restart=0
WQ Fixed Restart=0
WQ System Summary=0
WQ Write To DSS=0
Sorting and Armoring Iterations= 10
XS Update Threshold= 0.02
Bed Roughness Predictor= 0
Hydraulics Update Threshold= 0.02
Energy Slope Method= 1
Volume Change Method= 1
Sediment Retention Method= 0
Sediment TS Multiplier= 1
Warm Up Method= 0
XS Weighting Method= 0
Number of US Weighted Cross Sections= 1
Number of DS Weighted Cross Sections= 1
Upstream XS Weight=0
Main XS Weight=1
Downstream XS Weight=0
Number of DS XS's Weighted with US Boundary= 1
Upstream Boundary Weight= 1
Weight of XSs Associated with US Boundary= 0
Number of US XS's Weighted with DS Boundary= 1
Downstream Boundary Weight= 0.5
Weight of XSs Associated with DS Boundary= 0.5
Percentile Method= 0
Sediment Output Level= 3
Mass or Volume Output= 0
Output Increment Type= 1
Profile and TS Output Increment= 1
Transport Output Increment 1
XS Output Flag= 0
XS Output Increment= 10
Read HDF5 Sediment Hotstart= 0
Sediment Hotstart Type= 0
Write Gradation File= 0
Read Gradation Hotstart= 0
Write HDF5 File= 1
Write Binary Output= 1
Write DSS Sediment File= 0
DSS Sediment Output Type= 1
SV Curve= 0
Specific Gage Flag= 0
Subcell Erosion Methods= 0
Subcell Deposition Methods= 0
Advection Scheme= 1
Matrix Solver= 0
Implicit Weighting Factor= 1
Maximum Outer Loop Convergence Iterations= 5
Convergence Maximum Absolute= 0.001
Convergence RMSE= 0.0001
Grain Fractions Max Abs Error= 0.001
Max Subgrid Regions= 1
Max Subgrid Length Scale= 3.402823E+38
Initial Layer Thickness= 3.402823E+38
Min Layer Thickness= 3.402823E+38
Max Layer Thickness= 3.402823E+38
Number of Layers= 5

--- WOLFRN.f01 (steady flow) ---

Flow Title=Flow
Program Version=4.00
Number of Profiles=1
Profile Names=F01pct
River Rch & RM=WOLFRN,Main,2622
     638
Boundary for River Rch & Prof#=WOLFRN,Main      ,1
Up Type=0
Dn Type=3
Dn Slope=0.042355

--- WOLFRN.g01 (geometry) ---

Geom Title=Geometry
Program Version=6.31

River Reach=WOLFRN          ,Main
Reach XY= 30
     1686213.286      440280.1331686166.07805287440229.308684289
1686157.93851821440169.858975624     1686141.705      440145.776
     1686046.776      440085.297     1686044.096      440025.583
1686008.89691421439949.811701783     1685959.885      439900.414
     1685898.257      439866.346     1685846.964      439856.394
     1685802.561      439829.599     1685753.948      439785.962
     1685712.608      439728.162     1685636.817      439673.424
     1685542.653      439622.132     1685523.514      439591.892
     1685504.758      439455.239     1685475.284      439380.597
     1685375.378      439283.131     1685282.673      439229.303
     1685274.898      439214.949     1685271.907      439133.608
     1685193.557      438911.714     1685140.326      438831.569
     1685127.168      438786.712     1685002.764      438527.737
     1684957.907      438475.105     1684939.366      438436.228
1684905.73825807438313.574086023     1684897.358       438194.19

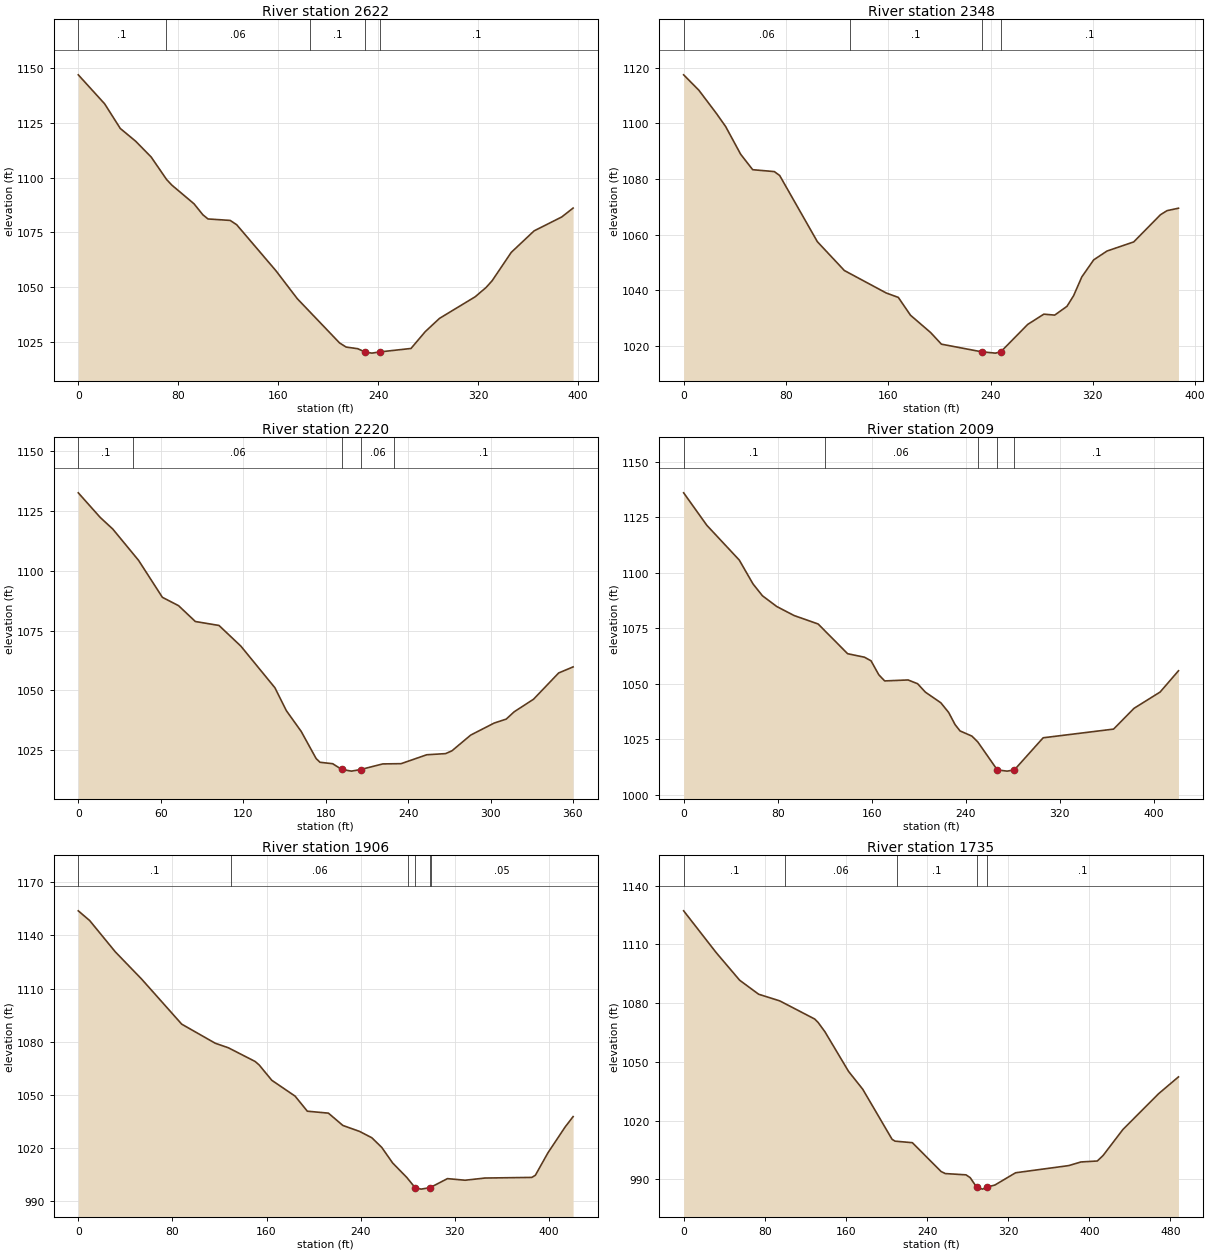
Type RM Length L Ch R = 1 ,2622    ,271.2,274,276.1
XS GIS Cut Line= 4
1686412.50441977440171.8170553351686300.59700573440201.293352701
1686152.75943422440321.4984980851686078.16137086440371.144478293
#Sta/Elev= 30
       0 1146.88    21.1 1133.64    33.6  1122.4    45.9 1116.58    58.3 1109.37
    70.7 1099.07    74.9 1096.52    92.6 1088.01    99.7 1082.98   103.8 1081.09
   121.5 1080.42   126.7 1078.48   158.2 1057.41   175.2 1044.71   209.1 1024.47
   214.3 1022.61   223.6 1021.86   229.3 1020.38   234.9 1019.84  241.03 1020.38
   266.2 1021.97   277.6 1029.65     289  1035.7   317.6 1045.58   326.3 1049.82
   331.1 1052.87   346.4 1065.82   364.7 1075.65   386.8 1081.99   395.9 1086.06
#Mann= 5 ,-1,0
       0      .1       0      70     .06       0  185.72      .1       0
   229.3    .045       0  241.03      .1       0
Bank Sta=229.3,241.03
XS Rating Curve= 0 ,0
Exp/Cntr(USF)=0,0
Exp/Cntr=0.3,0.1

Type RM Length L Ch R = 1 ,2348    ,128.7,128.2,126.2
XS GIS Cut Line= 3
 1686271.3617596440003.3211296231685992.63396041440096.411859433
1685921.31883991440156.294785041
#Sta/Elev= 30
       0 1117.44    11.9 1111.91    25.7 1103.52    32.9 1098.82    44.6  1088.9
      54 1083.35    70.9 1082.67    75.1 1081.27   104.6 1057.47   125.7 1047.12
   158.4 1039.06   167.9 1037.46   177.4 1031.07   193.2 1024.82   201.6 1020.66
  232.991017.921   243.8 1017.44     248  1017.9   269.1 1027.76   281.7 1031.44
   290.2  1031.1   299.8 1034.25     305 1038.09   311.4 1044.82   320.7 1050.95
   331.1 1054.12     352  1057.4   372.9 1067.16   378.1 1068.64     387 1069.51
#Mann= 4 ,-1,0
       0     .06       0     130      .1       0  232.99    .045       0
     248      .1       0
Bank Sta=232.99,248
XS Rating Curve= 0 ,0
Exp/Cntr(USF)=0,0
Exp/Cntr=0.3,0.1

Type RM Length L Ch R = 1 ,2220    ,214.5,211.1,205.2
XS GIS Cut Line= 2
1686186.10486551439863.3340013611685870.88724991440037.417597433
#Sta/Elev= 30
       0 1132.65      16 1122.33    25.1 1117.49    43.9 1104.37    61.2 1088.92
      73 1085.41    85.2 1078.79   102.4 1077.14   118.3  1068.5   143.1 1051.06
   151.4  1041.5   162.2 1032.81   173.1 1021.43   175.9 1019.87   185.1 1019.28
   191.81016.857   198.8 1016.17   205.5 1016.84   221.6 1019.19   234.9 1019.29
   253.6 1023.02   267.3  1023.5   271.9 1024.66   285.6 1031.26   302.6 1036.27
   311.4 1037.94   317.3 1041.04   331.3 1046.26   349.6 1057.26   360.1 1059.79
#Mann= 5 ,-1,0
       0      .1       0      40     .06       0   191.8    .045       0
   205.5     .06       0     230      .1       0
Bank Sta=191.8,205.5
XS Rating Curve= 0 ,0
Exp/Cntr(USF)=0,0
Exp/Cntr=0.3,0.1

Type RM Length L Ch R = 1 ,2009    ,98.7,102.9,104.9
XS GIS Cut Line= 4
1686051.06844923439675.8845402351685850.05686388439829.149035125
 1685827.0714985439884.1929364421685748.92085296439959.380116999
#Sta/Elev= 30
       0 1136.12    19.7  1121.5    47.3 1105.83      59 1095.06      67 1089.73
    79.2 1084.88    93.9 1080.82   114.4    1077   139.5  1063.6   153.8 1062.03
   159.4  1060.4     166 1054.11     171 1051.34   190.9 1051.77     199 1050.08
   205.6 1046.29   218.8 1041.47   225.4 1037.14   230.9 1031.64   235.1  1028.8
   245.2 1026.47   250.2 1023.84  266.831011.209   275.2 1010.68   281.3 1011.23
   305.8 1025.71   365.7 1029.62   383.1 1038.99   405.3 1046.33   420.9 1055.91
#Mann= 5 ,-1,0
       0      .1       0     120     .06       0     250      .1       0
  266.83    .045       0   281.3      .1       0
Bank Sta=266.83,281.3
XS Rating Curve= 0 ,0
Exp/Cntr(USF)=0,0
Exp/Cntr=0.3,0.1

Type RM Length L Ch R = 1 ,1906    ,173.5,171,166.9
BEGIN DESCRIPTION:
Structure XS 4
END DESCRIPTION:
XS GIS Cut Line= 2
1685979.34858364 439595.662105731685664.04864694439874.084856845
#Sta/Elev= 30
       0 1153.83     9.7 1148.33    31.5 1130.67    53.9 1115.28    87.9 1089.91
   116.4 1079.14   127.6 1076.56   150.3 1068.86   153.7 1066.91   164.5 1058.23
   184.3 1049.29   194.7 1040.79   212.6  1039.7   224.9 1032.75   239.1 1029.39
   249.5 1025.82     258 1020.34   267.2 1011.59   279.3 1003.38   286.3  997.65
   291.4  996.83  299.01997.6678   313.8 1002.75   328.8 1001.85   345.8 1003.09
   385.5 1003.44   388.5 1004.64   399.2  1017.3   413.8 1031.86   420.6 1037.74
#Mann= 6 ,-1,0
       0      .1       0     130     .06       0     280      .1       0
   286.3    .045       0  299.01      .1       0     300     .05       0
Bank Sta=286.3,299.01
XS Rating Curve= 0 ,0
Exp/Cntr(USF)=0,0
Exp/Cntr=0.3,0.1

Type RM Length L Ch R = 1 ,1735    ,32.5,31.7,31.2
BEGIN DESCRIPTION:
Structure XS 3
END DESCRIPTION:
XS GIS Cut Line= 5
1685839.58350733439490.1287995031685650.68009655439603.361967926
1685643.60302352439643.6468451531685631.08204817439705.707331693
1685650.68009655439867.935621067
#Sta/Elev= 30
       0 1127.11      32 1105.84    55.3 1091.65      74 1084.53    94.7 1081.16
   129.2 1071.89   132.6 1070.13   139.3 1065.39   162.6 1045.16   176.6 1036.04
   205.5 1010.51   208.4 1009.55   225.5 1008.76   253.9  994.03     258     993
   278.4  992.35   282.5  990.93  288.96986.0282   294.7  985.06   298.8  986.05
   298.8  986.06   306.9  987.15   327.3  993.41   379.7  997.07   391.8  998.93
   407.9  999.42   413.6 1002.24   433.1 1015.49   468.3 1033.76   487.9 1042.35
#Mann= 5 ,-1,0
       0      .1       0     100     .06       0     210      .1       0
  288.96    .045       0   298.8      .1       0
Bank Sta=288.96,298.8
XS Rating Curve= 0 ,0
Exp/Cntr(USF)=0,0
Exp/Cntr=0.3,0.1

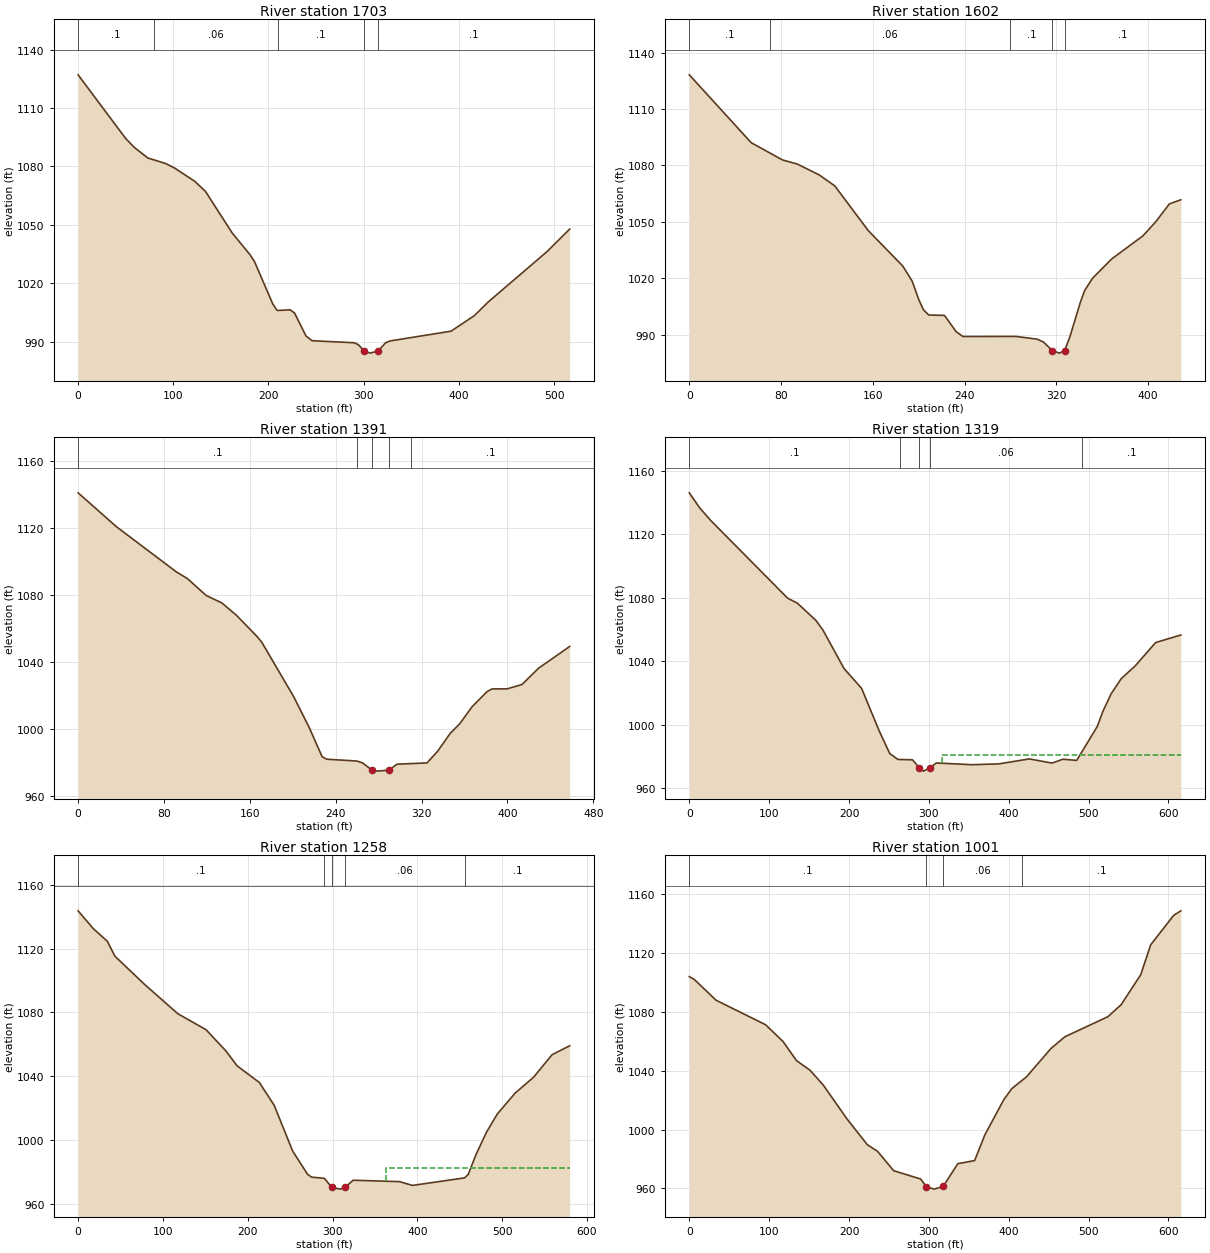
Type RM Length L Ch R = 1 ,1703    ,95.9,101.1,106.9
BEGIN DESCRIPTION:
Structure XS 2
END DESCRIPTION:
XS GIS Cut Line= 4
1685826.51814174439470.5307511221685621.82741421439594.651724201
 1685601.6849756439696.4526977351685628.03749539439867.686948986
#Sta/Elev= 30
       0 1127.09    49.8 1094.47    58.9 1089.85    73.1 1084.37    91.7 1081.54
     101 1079.29   122.6 1072.33   133.8 1067.17   161.9 1045.78   180.6 1034.63
   185.3 1031.12   204.4 1009.42   208.6 1006.24     210 1005.96   222.7 1006.31
   227.4 1004.65   239.4  992.87   245.8  990.41   290.1  989.36   294.3  988.39
   300.6   985.2   306.5  984.03  315.32985.1362   322.9  989.29   327.5  990.28
   391.8  995.31   416.1 1003.23   431.2 1010.47   492.7 1036.25   516.4 1047.77
#Mann= 5 ,-1,0
       0      .1       0      80     .06       0     210      .1       0
   300.6    .045       0  315.32      .1       0
Bank Sta=300.6,315.32
XS Rating Curve= 0 ,0
Exp/Cntr(USF)=0,0
Exp/Cntr=0.3,0.1

Type RM Length L Ch R = 1 ,1602    ,212.9,211.6,210.7
BEGIN DESCRIPTION:
Structure XS 1
END DESCRIPTION:
XS GIS Cut Line= 2
1685811.51716644439448.3048437171685435.14861043439653.291289401
#Sta/Elev= 30
       0 1128.16      54 1092.08    81.3 1082.93    94.1 1080.76   113.2 1075.01
   126.9 1069.13     156 1045.42   186.1 1026.59   194.3  1018.6   200.2 1008.59
   204.3 1003.21   208.8 1000.56   222.5 1000.35   232.7  991.68   238.6  989.13
   284.8  989.18   303.5   987.7     309  986.14  316.47981.6274   322.7   980.3
   327.3  981.66   331.8  988.89   340.9 1007.13   344.7 1013.52   351.7 1020.15
   368.3 1030.32   395.6 1042.65   406.7 1050.05   418.6 1059.58   428.6 1061.78
#Mann= 5 ,-1,0
       0      .1       0      70     .06       0     280      .1       0
  316.47    .045       0   327.3      .1       0
Bank Sta=316.47,327.3
XS Rating Curve= 0 ,0
Exp/Cntr(USF)=0,0
Exp/Cntr=0.3,0.1

Type RM Length L Ch R = 1 ,1391    ,72.9,71.3,70.1
BEGIN DESCRIPTION:
Structure XS 4
END DESCRIPTION:
XS GIS Cut Line= 2
1685726.58972506439251.2990414531685334.27779267439487.427229773
#Sta/Elev= 30
       0 1140.78    35.6 1120.64    91.6 1093.66   101.8 1089.72   119.3 1079.64
   133.9 1075.21   147.6 1067.78   166.3 1055.48     171 1051.91   200.9 1019.31
   215.5 1000.73   227.3  983.62   231.7  982.12   259.7  981.05     265  979.92
   273.7  975.68   278.3  975.03   289.4  975.58   297.1  979.16     325  979.91
     335  986.92   346.6  997.49   355.4 1003.15     367 1013.37   381.1 1022.45
   385.7    1024   399.7 1024.03   413.5 1026.62     429 1036.34   457.9 1049.27
#Mann= 5 ,-1,0
       0      .1       0     260     .06       0   273.7    .045       0
   289.4     .06       0     310      .1       0
Bank Sta=273.7,289.4
XS Rating Curve= 0 ,0
Exp/Cntr(USF)=0,0
Exp/Cntr=0.3,0.1

Type RM Length L Ch R = 1 ,1319    ,63.4,61.8,60.5
BEGIN DESCRIPTION:
Structure XS 3
END DESCRIPTION:
XS GIS Cut Line= 6
1685699.95077305439208.705932613 1685470.0971192439315.231675699
1685427.75565665439352.5324879461685332.31934423439327.665279781
1685289.30579498439296.0772045441685146.82341306439352.532487946
#Sta/Elev= 30
       0 1146.11      13 1136.64    26.9 1128.66   123.3 1079.69   135.3 1076.64
   158.5 1065.81   167.4 1059.66   193.8 1035.45   215.8 1022.96   237.9  996.11
   251.1  981.87   261.3  978.22   279.5  977.99     288  972.97   293.3  970.86
     301  972.97   309.5     976     354  974.91   387.6  975.42   425.8  978.55
   454.4  975.92   467.9  978.36   485.2  977.61     511  999.03   517.9 1008.38
   528.3 1019.54   541.1 1029.18   558.3 1037.04   584.1 1051.85   615.6 1056.57
#Mann= 5 ,-1,0
       0      .1       0  263.34     .06       0     288    .045       0
     301     .06       0  492.36      .1       0
#XS Ineff= 2 , 0
                          316.03          980.77
Permanent Ineff=
       F       F
Bank Sta=288,301
XS Rating Curve= 0 ,0
Exp/Cntr(USF)=0,0
Exp/Cntr=0.3,0.1

Type RM Length L Ch R = 1 ,1258    ,249.8,256.3,260.7
BEGIN DESCRIPTION:
Structure XS 2
END DESCRIPTION:
XS GIS Cut Line= 6
1685671.72313135439169.388860244 1685404.2326219439287.004033998
1685384.74210739 439312.54332887 1685338.3681246439299.773681434
1685295.35457534439268.1856061971685152.87219342439324.640889599
#Sta/Elev= 30
       0 1143.78    17.8 1132.67    34.5 1124.67    43.3 1115.39    78.2  1097.7
   117.6 1079.23   150.8 1069.22   174.4 1055.84   187.5 1046.53   213.7  1036.1
   231.2 1021.79     253  993.06   270.5  978.54   275.2  976.73   290.4  975.96
  299.23970.2522   309.2  969.19   314.7970.2942   324.3  974.77     379  973.89
   394.3  971.52   455.7  976.24     460   978.4   469.2  990.88   481.5 1004.86
   494.4 1016.38   515.4 1029.46     537 1039.36   558.9 1053.51   579.6 1059.13
#Mann= 5 ,-1,0
       0      .1       0     290     .06       0  299.23    .045       0
   314.7     .06       0  456.38      .1       0
#XS Ineff= 2 , 0
                          363.19          982.49
Permanent Ineff=
       F       F
Bank Sta=299.23,314.7
XS Rating Curve= 0 ,0
Exp/Cntr(USF)=0,0
Exp/Cntr=0.3,0.1

Type RM Length L Ch R = 1 ,1001    ,445.1,444.1,442
BEGIN DESCRIPTION:
Structure XS 1
END DESCRIPTION:
XS GIS Cut Line= 6
1685555.99358517439016.4034330841685311.81461158  439094.1253905
1685217.07136276439126.1722424181685145.68567875439150.144963503
1685059.99260867439172.8473459181684967.38485426439195.095660999
#Sta/Elev= 30
       0 1103.87     6.4 1101.89    33.5 1087.84    95.5 1071.19   117.4 1059.78
   134.2 1046.82     151 1040.36   167.8 1030.15   197.4 1007.23   222.9  989.68
   235.6  985.24   255.9  972.01   289.7  966.35  296.67961.2602   306.6  959.49
   317.9   961.3   336.2  976.77   357.3  978.89   369.9  996.13   393.6 1020.09
   403.7 1027.71   422.1 1035.71   452.9 1055.07   470.4 1063.04   524.2 1076.66
   540.7 1084.78   565.3 1105.16   577.7 1125.45   606.5 1145.49   615.5 1148.58
#Mann= 4 ,-1,0
       0      .1       0  296.67    .045       0   317.9     .06       0
  416.27      .1       0
Bank Sta=296.67,317.9
XS Rating Curve= 0 ,0
Exp/Cntr(USF)=0,0
Exp/Cntr=0.3,0.1

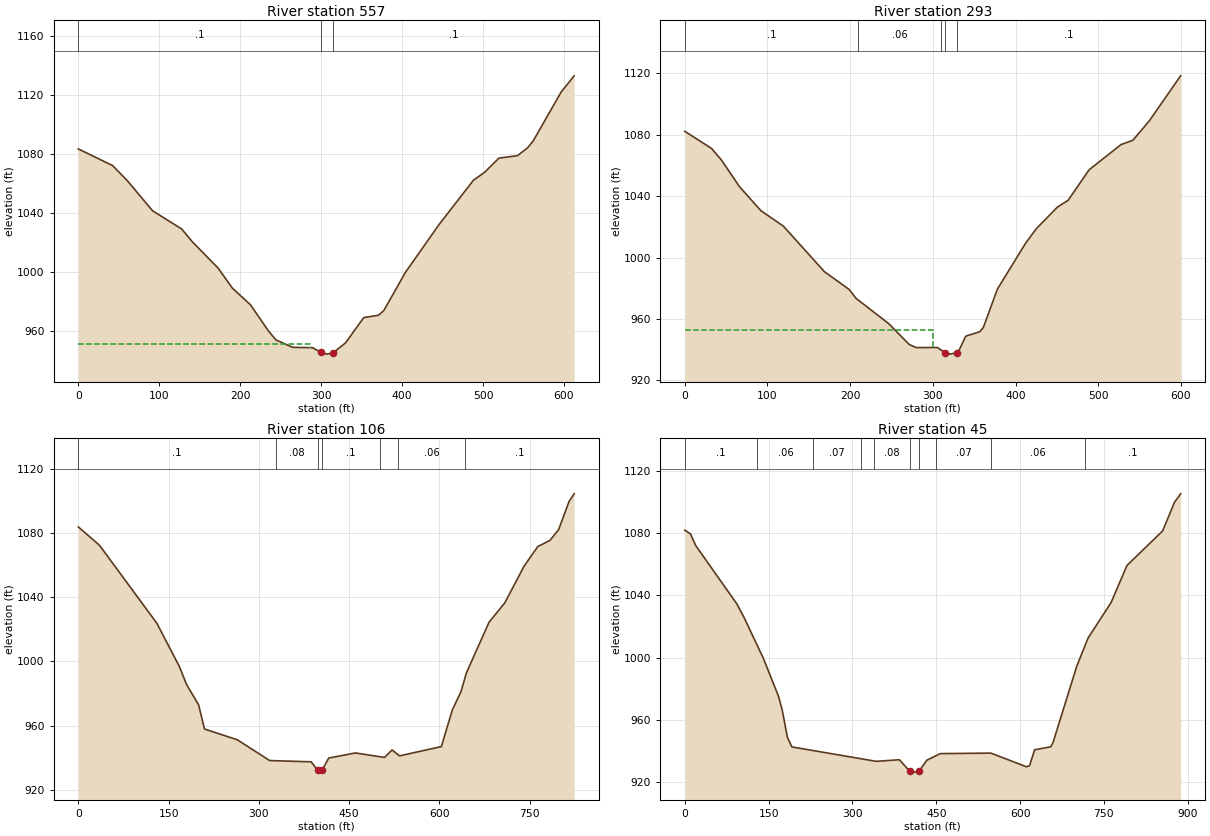
Type RM Length L Ch R = 1 ,557     ,263.9,264.5,265.5
XS GIS Cut Line= 6
1685361.99013978438566.4235552171685278.27409986438608.652801461
 1685200.1948597438648.1727355491685133.38856286438682.272732965
1685044.88283436438728.8211962951684818.12278919 438848.16872663
#Sta/Elev= 30
       0 1083.27    42.4 1071.95    60.3 1061.89    91.7 1041.34   127.6 1029.01
     141 1020.22   172.7 1002.47   190.3   988.9   212.8   977.5   235.1  959.66
   244.2  953.76   264.8  948.76   289.4  948.52  299.89945.2657   307.4  944.15
   315.2  945.24     330  951.74   352.6  968.91   370.7   970.5   377.4  973.69
     404  999.54   445.5 1031.91   488.2 1062.12   501.8 1067.37   519.5 1077.01
   542.5 1078.69   555.1 1084.11   561.8 1088.61   596.5  1121.9   612.5 1132.82
#Mann= 3 ,-1,0
       0      .1       0  299.89    .045       0   315.2      .1       0
#XS Ineff= 2 , 0
          286.35  950.68
Permanent Ineff=
       F       F
Bank Sta=299.89,315.2
XS Rating Curve= 0 ,0
Exp/Cntr(USF)=0,0
Exp/Cntr=0.3,0.1

Type RM Length L Ch R = 1 ,293     ,186.9,187.2,187.9
BEGIN DESCRIPTION:
Structure XS 4
END DESCRIPTION:
XS GIS Cut Line= 2
1685258.33599678438365.4613243431684696.60426746438575.384703246
#Sta/Elev= 30
       0 1082.24    32.3  1071.1    44.5  1063.4    66.4 1045.99      92 1030.55
   119.1 1020.51   168.9  990.77   198.8  979.19   207.3   973.3   246.6  956.96
   271.4  943.37   279.9  941.33   305.6  941.38     315  937.87   321.2  937.06
   328.7  937.98   331.2     939   339.8  948.76   356.8  951.67   361.1  954.44
   378.1  979.42   412.3 1009.41   425.1 1018.73   450.7 1032.86   463.6 1037.27
     489 1057.16   527.6 1073.59   541.9 1076.36   561.8 1089.02   599.7 1118.38
#Mann= 5 ,-1,0
       0      .1       0     210     .06       0     310      .1       0
     315    .045       0   328.7      .1       0
#XS Ineff= 2 , 0
          300.66  952.81
Permanent Ineff=
       F       F
Bank Sta=315,328.7
XS Rating Curve= 0 ,0
Exp/Cntr(USF)=0,0
Exp/Cntr=0.3,0.1

Type RM Length L Ch R = 1 ,106     ,63.9,60.9,59.5
BEGIN DESCRIPTION:
Structure XS 3
END DESCRIPTION:
XS GIS Cut Line= 6
1685274.10099361438267.5523966331685071.64524479438212.789776049
1684988.67157724438266.7226599571684880.80580942438305.720283706
1684706.56110757438269.2118699841684586.24928962438454.243148622
#Sta/Elev= 30
       0 1084.02    35.2 1072.53   130.5 1023.86   167.8  996.94   180.2  985.37
   199.8  973.05   209.7  957.82   264.1  951.12     318  938.13     387  937.34
   397.7  932.16   399.5   930.9  405.12932.0864   416.1  939.68   460.4  942.88
   508.8  940.08   521.5  944.75   533.9  941.04   603.4  946.86   621.6  969.73
     636  981.11   645.1  992.95   682.7 1024.55   708.7  1036.5   740.9 1059.52
   763.7 1071.75   783.9 1075.62   798.2 1082.26   815.7 1099.99   824.1 1104.67
#Mann= 7 ,-1,0
       0      .1       0  328.69     .08       0   397.7    .045       0
  405.12      .1       0  501.79     .07       0  531.79     .06       0
  643.36      .1       0
Bank Sta=397.7,405.12
XS Rating Curve= 0 ,0
Exp/Cntr(USF)=0,0
Exp/Cntr=0.3,0.1

Type RM Length L Ch R = 1 ,45      ,,,
BEGIN DESCRIPTION:
Structure XS 2
END DESCRIPTION:
XS GIS Cut Line= 6
1685279.07941367438246.8089797451685060.02893133438163.005575519
1684884.12475613438245.1495063941684776.25898831438241.000823017
1684700.75295084438216.9384594271684557.20850598438445.945781867
#Sta/Elev= 30
       0 1081.85    10.3 1079.41    19.5 1072.01    93.1 1034.53     106 1025.81
   140.4  999.68   167.7  975.13   174.3  966.33   183.7  948.67   191.6   942.6
   342.4  933.35     384  934.37  402.16927.1134   411.9  926.41   419.4  927.11
   433.1  934.07   457.2  938.31   547.7  938.62   611.4  929.85   616.9   930.5
   625.9  940.77   654.8  942.68     659  945.53   701.3  994.42   721.6 1012.57
   762.8 1035.38   791.1 1059.14   855.1  1081.4   876.1 1099.67   887.2 1105.21
#Mann= 10 ,-1,0
       0      .1       0     130     .06       0     230     .07       0
  314.53      .1       0  339.24     .08       0  402.16    .045       0
   419.4     .08       0  449.09     .07       0   547.7     .06       0
  716.94      .1       0
Bank Sta=402.16,419.4
XS Rating Curve= 0 ,0
Exp/Cntr(USF)=0,0
Exp/Cntr=0.3,0.1
LCMann Table=0

Chan Stop Cuts=-1
Use User Specified Reach Order=0
Composite Channel Slope=5